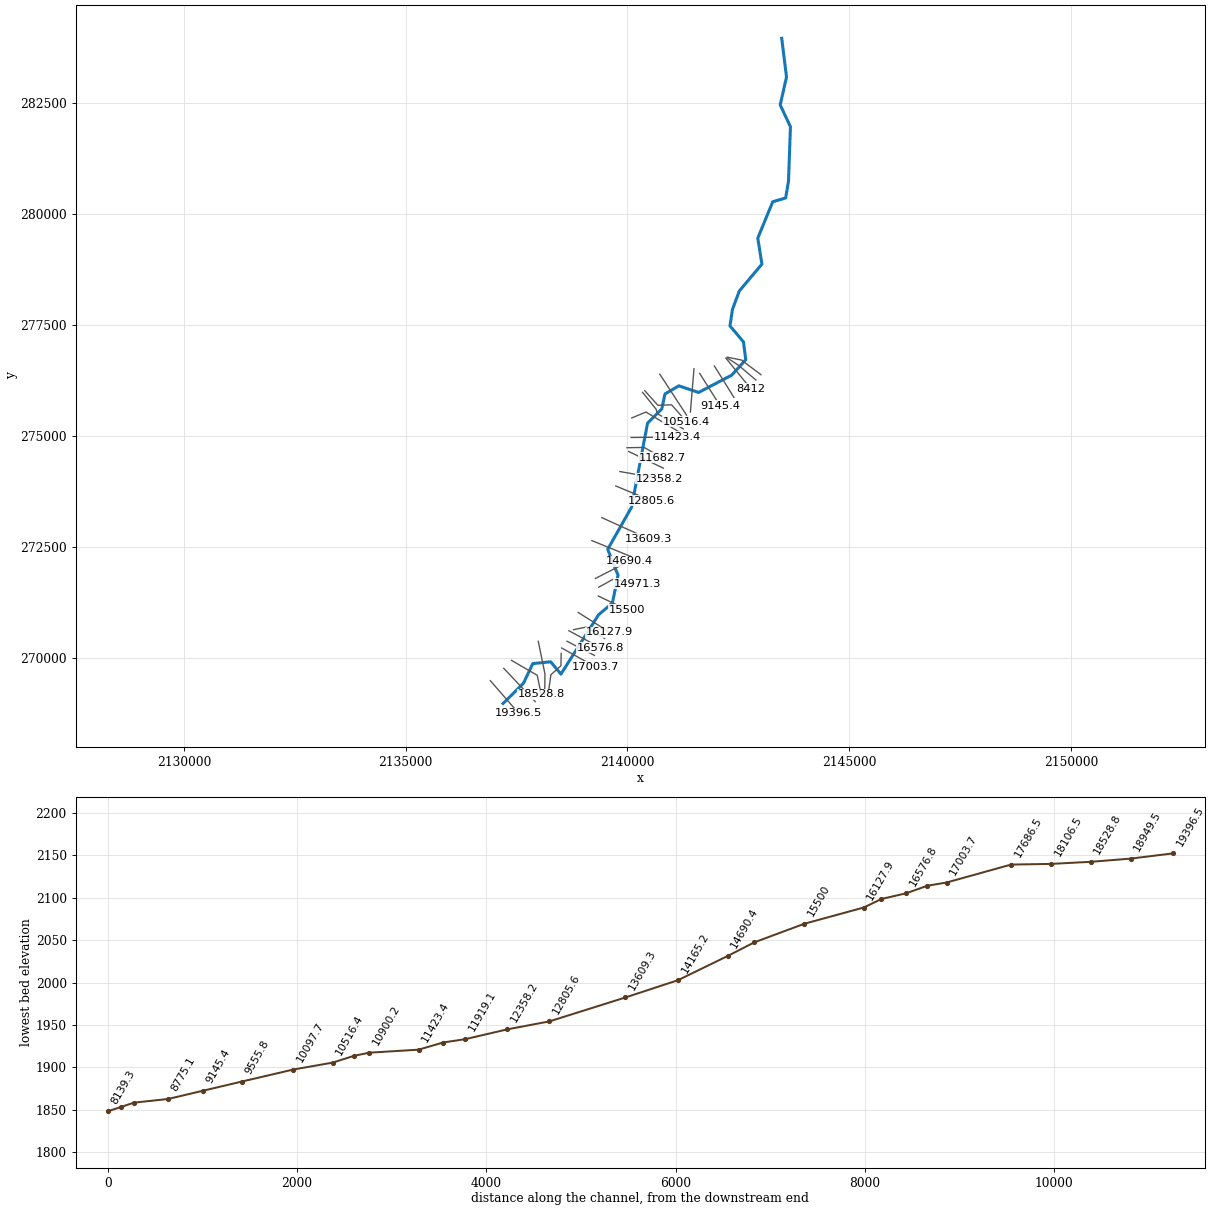
--- HowardCkT1.prj (project) ---

Proj Title=HowardCkT1
Current Plan=p01
Geom File=g01
Flow File=f01
Plan File=p01
DSS Export Rating Curves=0
DSS Export Rating Curve Sorted=0
DSS Export Volume Flow Curves=0
DXF OffsetX=0
DXF OffsetY=0
DXF ScaleX=0
DXF ScaleY=0

--- HowardCkT1.p01 (plan) ---

Plan Title=Floodplain
Program Version=4.00
Geom File=g01
Flow File=f01
K Sum by GR=0
Std Step Tol=0.01
Critical Tol=0.01
Num of Std Step Trials=20
Max Error Tol=0.3
Flow Tol Ratio=0.001
Split Flow NTrial=30
Split Flow Tol=0.02
Split Flow Ratio=0.02
Log Output Level=0
Friction Slope Method=1
Unsteady Friction Slope Method=2
Unsteady Bridges Friction Slope Method=1
Global Log Level=0
CheckData=False
Run HTab=0
Run UNet=0
Run PostProcess=0
UNET Theta=0
UNET Theta Warmup=0
UNET ZTol=0
UNET ZSATol=0
UNET MxIter=0
UNET MaxInSteps=0
UNET DtIC=0
UNET DtMin=0
UNET MaxCRTS=0
UNET WFStab=0
UNET SFStab=0
UNET WFX=0
UNET SFX=0
UNET DSS MLevel=0
UNET DZMax Abort=0
UNET Convert EG Bridges=0
UNET Use Existing IB Tables=0
UNET Froude Limit=0
UNET Froude Power=0
Write IC File=0
Echo Input=False
Echo Output=False
Write Detailed=0

--- HowardCkT1.f01 (steady flow) ---

Flow Title=NFF Regression Equation
Program Version=4.00
Number of Profiles=1
Profile Names=P100yr
River Rch & RM=HowardCkT1,Main      ,19396.5
541.7827
River Rch & RM=HowardCkT1,Main      ,17686.5
558.0776
River Rch & RM=HowardCkT1,Main      ,17003.7
651.5766
River Rch & RM=HowardCkT1,Main      ,15500
701.8601
River Rch & RM=HowardCkT1,Main      ,10516.4
777.5205
River Rch & RM=HowardCkT1,Main      ,10097.7
941.5183
River Rch & RM=HowardCkT1,Main      ,8775.1
1015.591
River Rch & RM=HowardCkT1,Main      ,5453
1124.252
River Rch & RM=HowardCkT1,Main      ,4766.6
1198.597
River Rch & RM=HowardCkT1,Main      ,256.9
1319.484
Boundary for River Rch & Prof#=HowardCkT1,Main      ,1
Up Type=0
Dn Type=3
Dn Slope=0.018814

--- HowardCkT1.g01 (geometry) ---

Geom Title=USGS 10m DEM
Program Version=4.10

River Reach=HowardCkT1      ,Main
Reach XY= 30
     2137195.447      268969.808     2137656.384      269429.183
     2137865.759      269869.808     2138268.884      269910.433
     2138500.134      269632.308     2139350.134       270971.37
     2139661.072       271233.87     2139787.634      271860.433
     2139554.822      272444.808     2140092.322      273393.245
     2140453.259      275286.995     2140775.134      275607.308
     2140845.424      275945.291      2141157.74      276129.546
     2141606.384      275980.745     2142353.259       276371.37
     2142668.884      276718.245     2142616.513      277121.638
     2142313.204      277478.491     2142366.883      277846.694
     2142522.105      278265.854     2143033.675       278874.14
     2142939.197       279458.87     2143277.745      280279.015
     2143568.884      280363.558     2143632.947       280746.37
     2143676.413      281969.649     2143445.492      282459.717
     2143587.634       283090.12     2143479.904      283961.824

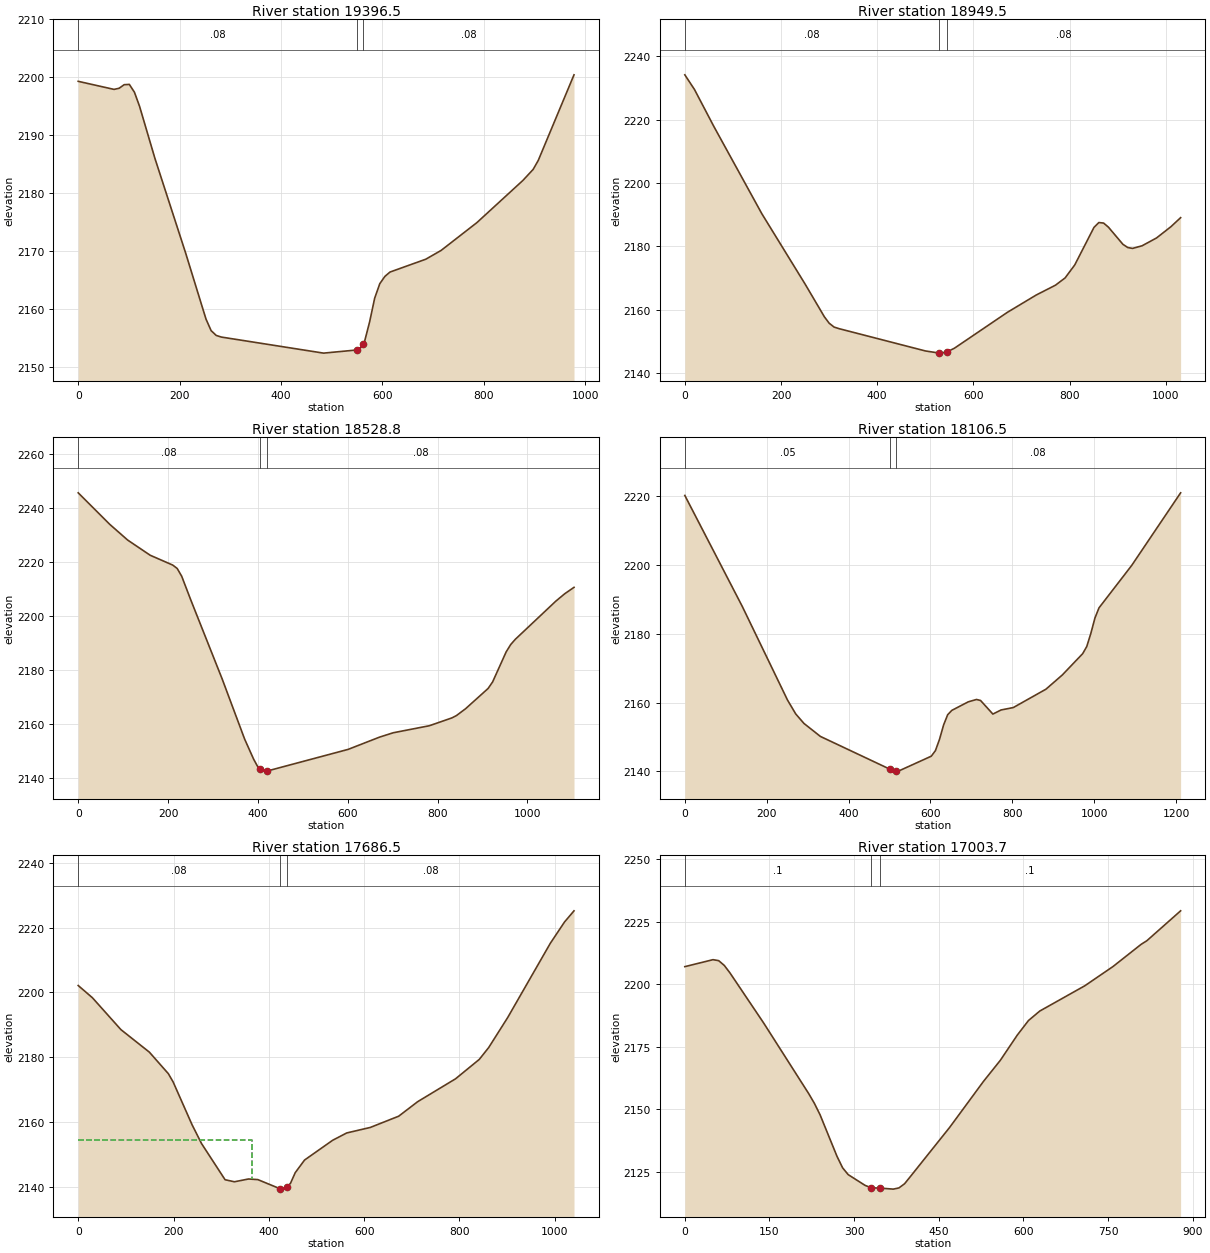
Type RM Length L Ch R = 1 ,19396.5 ,446,447,447.5
XS GIS Cut Line= 2
     2136907.516      269485.255     2137548.835      268747.229
#Sta/Elev= 30
       0  2199.3    70.6 2197.91    80.6  2198.1    90.7 2198.72   100.8 2198.77
   110.9 2197.42     121 2194.99   151.2 2186.04   211.7 2169.74     252 2158.31
   262.1 2156.32   272.2 2155.49   282.2 2155.21   483.8 2152.44  548.92 2152.98
   554.4 2153.07  562.06 2154.01   564.5 2154.38   574.6  2157.8   584.6  2161.9
   594.7 2164.41   604.8 2165.67   614.9 2166.42   685.4 2168.63   715.7 2170.15
   786.2 2174.94   876.9 2182.21   897.1 2184.11   907.2 2185.66   977.7 2200.42
#Mann= 3 , 0 , 0
       0     .08       0  548.92    .045       0  562.06     .08       0
Bank Sta=548.92,562.06
XS Rating Curve= 0 ,0
Exp/Cntr=0.3,0.1

Type RM Length L Ch R = 1 ,18949.5 ,413.8,420.7,427.5
XS GIS Cut Line= 2
     2137210.978      269762.107     2137919.296      269013.148
#Sta/Elev= 30
       0 2234.17      20 2229.56      60 2217.97   160.1 2190.32   250.2 2168.07
   290.2 2157.76   300.2 2155.73   310.3 2154.53   320.3 2154.04   500.4 2146.98
   529.3 2146.31   530.4  2146.3   544.3 2146.63   560.5 2147.85   670.6 2159.18
   730.6 2164.65   770.6 2167.75   790.6 2170.04   810.7 2174.15   850.7 2186.01
   860.7 2187.53   870.7 2187.36   880.7 2186.07   910.8 2180.66   920.8 2179.65
   930.8 2179.36   950.8  2180.2   980.8 2182.67  1010.8 2186.24  1030.8 2189.07
#Mann= 3 , 0 , 0
       0     .08       0   529.3    .045       0   544.3     .08       0
Bank Sta=529.3,544.3
XS Rating Curve= 0 ,0
Exp/Cntr=0.3,0.1

Type RM Length L Ch R = 1 ,18528.8 ,440.8,422.3,402.5
XS GIS Cut Line= 3
     2137385.155       269942.09     2137965.743      269605.348
     2138052.831      269181.519
#Sta/Elev= 30
       0  2245.7    70.1 2234.04   110.2 2228.18   160.3 2222.56   210.4 2218.92
   220.4 2217.66   230.4 2214.79   250.4  2206.1   320.6 2176.67   370.6 2154.39
   390.7 2146.92   400.7 2143.88   405.5 2143.23   410.7 2142.53   420.5 2142.56
     601 2150.59   671.2 2155.15   701.4 2156.75   781.9 2159.36   832.2 2162.27
   842.2 2163.13   862.4 2165.65   912.7 2173.18   922.7  2175.6   952.9 2186.75
     963 2189.46     973 2191.36  1063.6 2205.57  1083.7 2208.34  1103.9 2210.66
#Mann= 3 , 0 , 0
       0     .08       0   405.5    .045       0   420.5     .08       0
Bank Sta=405.5,420.5
XS Rating Curve= 0 ,0
Exp/Cntr=0.3,0.1

Type RM Length L Ch R = 1 ,18106.5 ,444.8,420,395.6
XS GIS Cut Line= 3
     2137988.967      270371.725      2138139.92      269634.378
     2138134.114      269175.713
#Sta/Elev= 30
       0  2220.2   140.5  2187.9   250.9 2160.71     271 2156.67     291 2153.92
   331.2 2150.14   500.9 2140.62   515.9 2140.06   521.8 2140.05   602.1 2144.39
   612.2    2146   622.2 2149.28   632.2 2153.46   642.2 2156.45   652.3 2157.71
   692.4 2160.19   712.5 2160.88   722.5 2160.59   752.6 2156.64   772.6 2157.83
   802.5 2158.53   882.3 2163.87   922.2    2168     972  2174.2     982 2176.28
     992 2180.11  1001.9 2184.54  1011.9 2187.52  1091.7 2199.84  1211.3 2220.96
#Mann= 3 , 0 , 0
       0     .05       0   500.9    .045       0   515.9     .08       0
Bank Sta=500.9,515.9
XS Rating Curve= 0 ,0
Exp/Cntr=0.3,0.1

Type RM Length L Ch R = 1 ,17686.5 ,636.9,682.8,727.8
XS GIS Cut Line= 4
      2138505.69      270098.849     2138499.884      269820.166
     2138273.455       269616.96      2138209.59      269164.101
#Sta/Elev= 30
       0 2202.15    29.9 2198.36    89.6 2188.53   149.3 2181.57   189.2 2174.91
   199.1 2172.39   238.9 2159.15   258.8 2153.33   308.2 2142.16   327.8 2141.53
   357.3 2142.39   376.9  2142.2   423.4 2139.39     426 2139.26   438.4 2139.86
   445.6 2141.11   455.4 2144.35     475 2148.25   533.9 2154.35   563.4 2156.61
   612.8 2158.31   672.5 2161.79   712.2 2166.26   791.8 2173.34   841.5 2179.32
   861.4 2183.01   901.1 2192.24   990.6 2215.19  1020.4 2221.77  1040.3 2225.22
#Mann= 3 , 0 , 0
       0     .08       0   423.4    .045       0   438.4     .08       0
#XS Ineff= 2 , 0
          365.28 2154.49
Permanent Ineff=
       F       F
Bank Sta=423.4,438.4
XS Rating Curve= 0 ,0
Exp/Cntr=0.3,0.1

Type RM Length L Ch R = 1 ,17003.7 ,201.8,202.7,203.3
XS GIS Cut Line= 2
     2138517.302      270220.772     2139283.679      269791.137
#Sta/Elev= 30
       0 2207.07    49.9 2209.86    59.9 2209.48    69.9 2207.57    79.9  2204.6
   139.8  2184.5   219.6 2156.26   229.6 2152.39   239.6 2147.85   269.6 2131.24
   279.6 2126.61   289.5 2123.88   319.5 2119.57   330.6 2118.61   345.6  2118.5
   369.4 2118.08   379.4 2118.56   389.4 2120.22   399.4 2123.02   469.2 2142.74
   529.2 2161.16   559.1  2169.6     589 2179.64     609 2185.52     629 2189.31
   708.9 2199.43   758.8 2207.12   808.7 2216.01   818.7 2217.43   878.6  2229.4
#Mann= 3 , 0 , 0
       0      .1       0   330.6    .045       0   345.6      .1       0
Bank Sta=330.6,345.6
XS Rating Curve= 0 ,0
Exp/Cntr=0.3,0.1

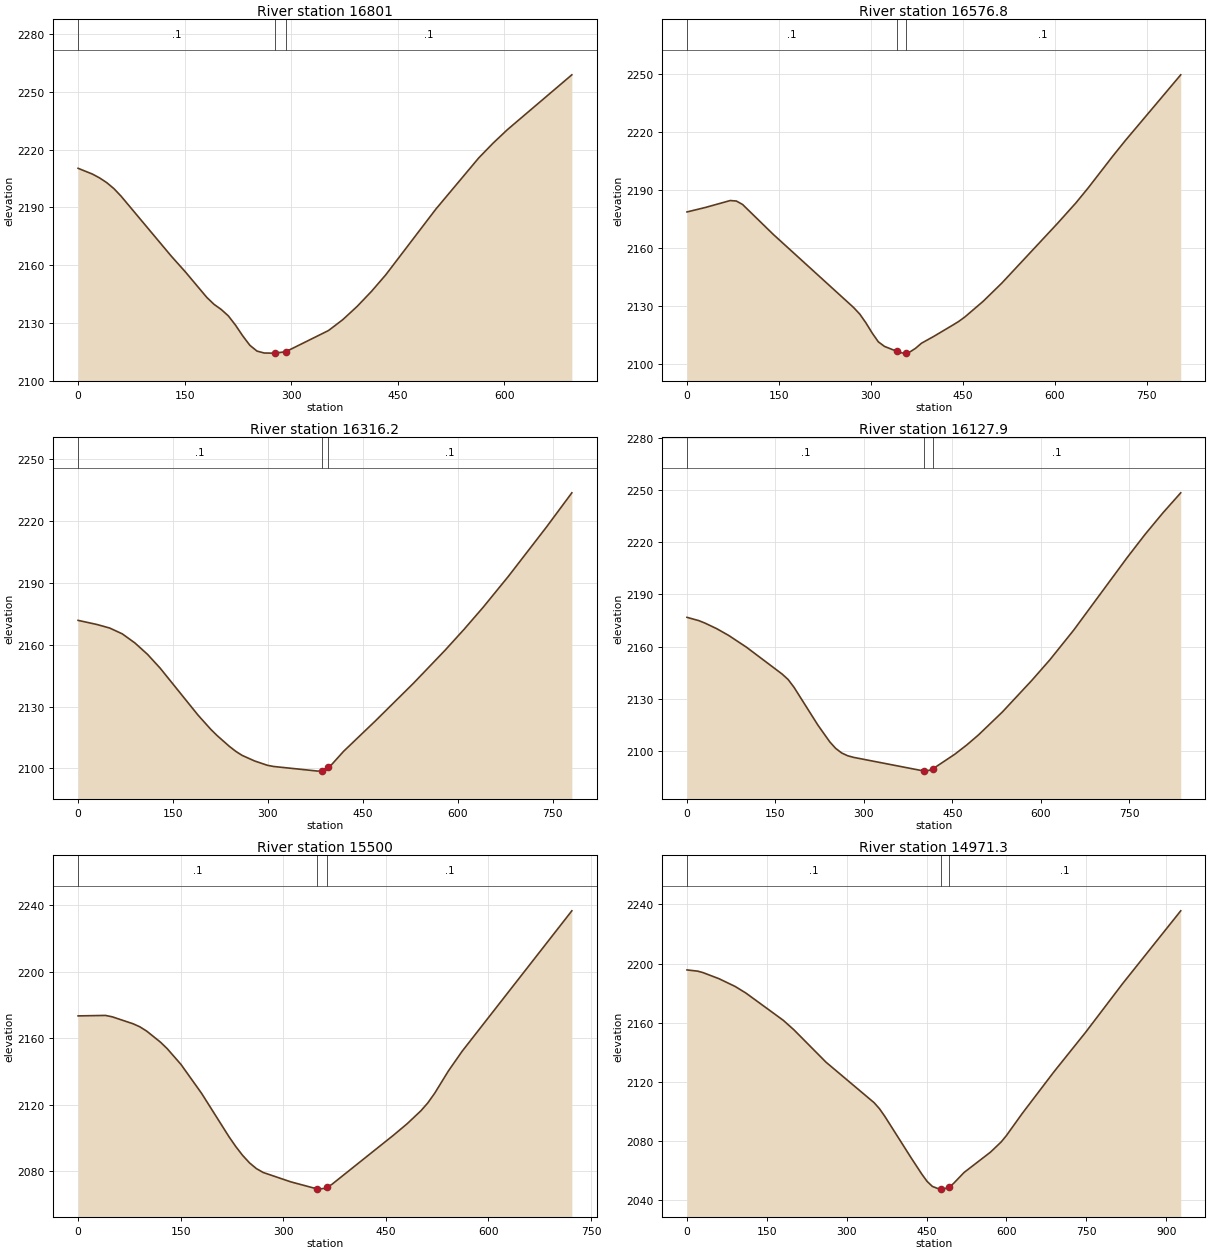
Type RM Length L Ch R = 1 ,16801   ,224.7,224.3,223.8
XS GIS Cut Line= 2
      2138638.06      270372.583     2139255.627       270053.62
#Sta/Elev= 30
       0 2210.33    20.2 2207.34    30.2 2205.35    40.3  2202.9    50.4 2199.78
    60.4  2195.9     131 2164.77   151.1 2156.47   181.3  2143.2   191.4 2139.63
   201.5 2136.97   211.5 2133.65   221.6 2128.83   231.7 2123.29   241.8 2118.36
   251.8 2115.35   261.9 2114.35     272 2114.28   277.2 2114.32   292.2 2114.98
   352.6 2126.04   372.7  2131.7   392.9 2138.58     413 2146.36   433.2    2155
   503.7 2189.15   564.1 2215.76   584.3 2223.44   604.4 2230.43   695.1 2258.92
#Mann= 3 , 0 , 0
       0      .1       0   277.2    .045       0   292.2      .1       0
Bank Sta=277.2,292.2
XS Rating Curve= 0 ,0
Exp/Cntr=0.3,0.1

Type RM Length L Ch R = 1 ,16576.8 ,261.7,260.6,259.5
XS GIS Cut Line= 2
     2138679.867      270609.766     2139388.185      270226.578
#Sta/Elev= 30
       0 2178.54    30.2 2180.88    70.5 2184.45    80.5  2184.2    90.6 2182.43
   140.9 2166.86   271.8 2129.01   281.9 2125.57   291.9 2121.04     302 2115.82
   312.1 2111.23   322.1 2108.87   341.8 2106.37   352.3 2105.38   356.8 2105.55
   362.4 2105.76   372.5 2107.81   382.5 2110.52   402.7 2114.09   432.9 2119.79
   442.9 2121.74     453 2124.06   483.2 2132.28   513.4 2141.64     604  2172.5
   634.2 2183.18   654.3 2190.97   694.6 2207.52   714.7 2215.45   805.3  2249.6
#Mann= 3 , 0 , 0
       0      .1       0   341.8    .045       0   356.8      .1       0
Bank Sta=341.8,356.8
XS Rating Curve= 0 ,0
Exp/Cntr=0.3,0.1

Type RM Length L Ch R = 1 ,16316.2 ,188.5,188.2,187.9
XS GIS Cut Line= 3
     2138783.969      270633.861     2139067.303      270691.546
     2139486.366      270435.358
#Sta/Elev= 30
       0 2171.87    29.9 2169.86    49.8 2168.16    69.8 2165.33    89.7 2160.93
   109.7 2155.37   129.6  2148.7   189.4 2125.92   209.4 2119.06   219.4 2116.01
   239.3 2110.62   249.3 2108.25   259.2 2106.31   279.2 2103.56   299.2 2101.49
   309.2 2100.91   379.4 2098.66  385.18 2098.96   389.4 2099.15  395.69 2100.53
   399.4 2101.39   419.5 2108.25   469.6 2122.98   529.7 2141.24   579.8 2157.31
   609.9 2167.49     640 2178.17   680.1 2193.28   740.2 2217.19   780.3 2233.81
#Mann= 3 , 0 , 0
       0      .1       0  385.18    .045       0  395.69      .1       0
Bank Sta=385.18,395.69
XS Rating Curve= 0 ,0
Exp/Cntr=0.3,0.1

Type RM Length L Ch R = 1 ,16127.9 ,625.6,627.9,630.1
XS GIS Cut Line= 2
     2138888.879      271021.984     2139597.197      270574.931
#Sta/Elev= 30
       0  2176.8    20.2  2174.9    30.3 2173.53    50.5 2170.28    70.6 2166.44
   100.9 2159.66   161.5 2144.22   171.6  2141.1   181.6 2136.63     222 2114.99
   242.2 2105.34   252.3 2101.56   262.4 2098.95   272.5 2097.36   282.6 2096.43
     402 2088.59   403.7 2088.53   413.8  2089.2     417 2089.81   454.1 2098.18
   474.3 2103.46   494.5 2109.31   534.8  2122.4   585.3 2140.73   615.6 2152.43
     656 2169.45   746.8 2211.14     777 2224.37   807.3 2236.74   837.6 2248.27
#Mann= 3 , 0 , 0
       0      .1       0     402    .045       0     417      .1       0
Bank Sta=402,417
XS Rating Curve= 0 ,0
Exp/Cntr=0.3,0.1

Type RM Length L Ch R = 1 ,15500   ,522.8,528.7,534.5
XS GIS Cut Line= 2
     2139341.738      271393.561     2139991.997      271080.043
#Sta/Elev= 30
       0 2173.57    40.1 2173.85    50.1    2173    80.2 2168.87    90.2 2167.02
   100.3 2164.42   120.3 2157.83   130.3 2153.86   150.4 2144.39   180.5 2127.03
   220.6 2100.92   230.6 2094.97   240.6 2089.66   250.7 2085.16   260.7 2081.73
   270.7 2079.39   310.8 2073.79   349.4 2069.52   350.9 2069.39     361 2069.89
   364.4 2070.69     371 2072.23   461.2 2101.85   481.3 2108.78   501.3 2116.54
   511.3 2121.23   521.4 2127.07   541.4 2140.45   561.5  2152.3   721.9 2236.76
#Mann= 3 , 0 , 0
       0      .1       0   349.4    .045       0   364.4      .1       0
Bank Sta=349.4,364.4
XS Rating Curve= 0 ,0
Exp/Cntr=0.3,0.1

Type RM Length L Ch R = 1 ,14971.3 ,265.9,280.9,295.9
XS GIS Cut Line= 3
     2139353.349      271590.961     2139678.479      271770.943
     2140224.232      271666.437
#Sta/Elev= 30
       0 2195.68    20.1 2194.85    30.1 2193.86    60.3 2189.71    90.4 2184.51
   110.5 2180.08   180.8 2161.62   200.9 2155.16   261.1  2133.3   351.5 2105.89
   361.6 2101.79   371.6 2096.64   421.2  2068.5   441.1 2057.57     451 2052.67
   460.9 2049.29   470.8 2047.91   477.3 2047.62   480.8 2047.46   492.3 2048.69
   500.6  2051.3   520.5 2058.75   570.1  2072.5   589.9  2079.3   599.8 2083.62
   629.6  2098.6   689.2  2126.8   748.7 2153.52   818.1 2186.39   927.3 2235.64
#Mann= 3 , 0 , 0
       0      .1       0   477.3    .045       0   492.3      .1       0
Bank Sta=477.3,492.3
XS Rating Curve= 0 ,0
Exp/Cntr=0.3,0.1

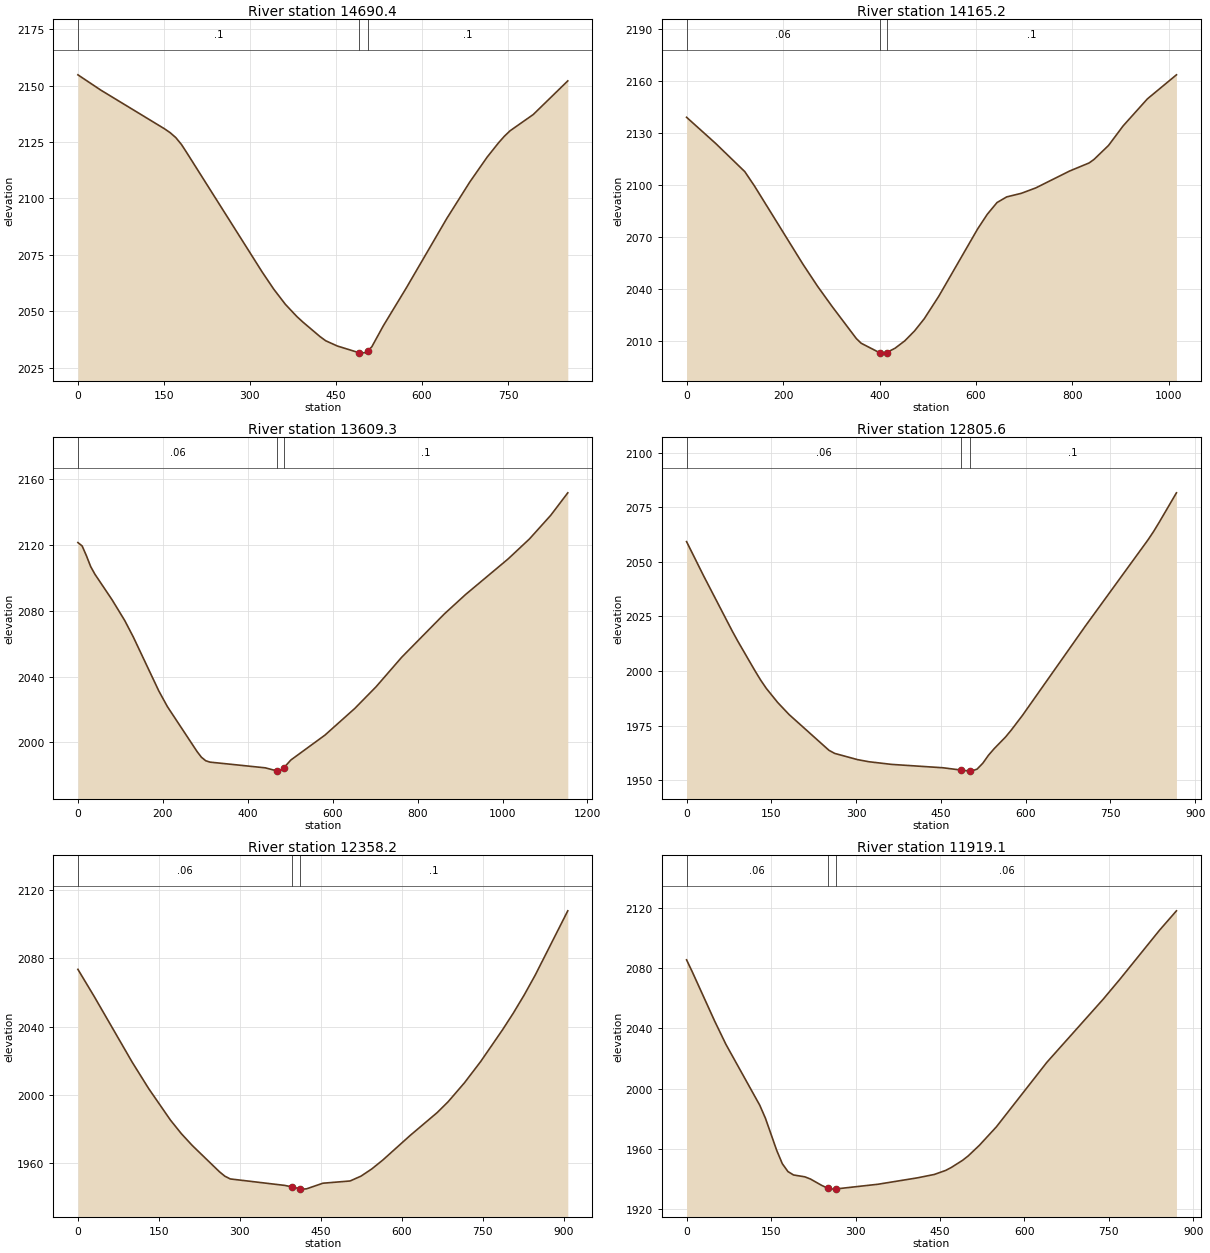
Type RM Length L Ch R = 1 ,14690.4 ,544.5,525.2,505.6
XS GIS Cut Line= 2
     2139277.873      271788.361     2140038.444      272177.355
#Sta/Elev= 30
       0  2154.8    40.2 2147.98   150.8  2130.9   160.8 2129.16   170.8 2126.94
   180.9 2123.79     191 2119.81   321.6 2067.26   341.7 2059.69   361.8 2053.02
   381.9 2047.59     392 2045.23   422.1 2038.74   432.2 2036.85   452.3 2034.55
   490.9  2031.5   492.5 2031.38   502.5 2031.66   505.9 2032.52   512.6 2034.22
   532.7 2043.54   572.9 2060.38   643.2 2091.06   683.4 2107.27   713.6 2118.28
   733.7  2124.7   743.7 2127.56   753.8 2130.01     794 2137.18   854.3 2152.11
#Mann= 3 , 0 , 0
       0      .1       0   490.9    .045       0   505.9      .1       0
Bank Sta=490.9,505.9
XS Rating Curve= 0 ,0
Exp/Cntr=0.3,0.1

Type RM Length L Ch R = 1 ,14165.2 ,556.8,555.9,555
XS GIS Cut Line= 2
     2139196.591      272641.826     2140137.144      272258.638
#Sta/Elev= 30
       0 2139.11    60.3    2124   120.7 2107.71   140.8  2099.4   241.3 2054.21
   271.5  2041.5   301.7 2029.81     352 2011.24     362 2008.55     400  2003.1
   402.2 2002.84     415 2003.16   432.4 2005.71   452.5 2009.96   472.6 2015.65
   492.7 2022.68   522.9 2035.72   603.3 2074.54   623.4 2083.05   643.6 2089.84
   663.7 2093.11   693.8 2095.16     724  2098.3   794.4 2108.09   834.6 2112.73
   844.7 2114.76   874.8 2122.84     905 2134.11   955.3 2149.73  1015.6 2163.64
#Mann= 3 , 0 , 0
       0     .06       0     400    .045       0     415      .1       0
Bank Sta=400,415
XS Rating Curve= 0 ,0
Exp/Cntr=0.3,0.1

Type RM Length L Ch R = 1 ,13609.3 ,802.9,803.7,804.5
XS GIS Cut Line= 2
      2139423.02       273158.55     2140473.885      272682.467
#Sta/Elev= 30
       0 2121.51      10 2119.45    20.1 2113.46    30.1 2106.88    40.1 2102.24
    80.3 2086.77   110.4 2074.03   130.4 2064.09   190.6  2031.2   210.7 2021.72
   280.9 1994.25   290.9 1990.89     301 1988.76     311 1987.92   441.4 1984.44
   469.2 1982.53   471.5 1982.44   481.5 1983.54   484.2 1984.28   501.6 1989.22
   581.8 2004.35   652.1 2020.59   702.2 2033.77   762.4 2051.69   862.8 2078.04
   912.9 2089.88  1013.2 2111.56  1063.4 2123.71  1113.6 2138.12  1153.7 2151.78
#Mann= 3 , 0 , 0
       0     .06       0   469.2    .045       0   484.2      .1       0
Bank Sta=469.2,484.2
XS Rating Curve= 0 ,0
Exp/Cntr=0.3,0.1

Type RM Length L Ch R = 1 ,12805.6 ,442.3,447.4,452.3
XS GIS Cut Line= 2
     2139736.538      273872.674      2140537.75      273541.738
#Sta/Elev= 30
       0 2059.25    30.2 2043.58    80.6 2018.44    90.7 2013.68     121 2000.17
     131 1995.93   141.1 1992.09   161.3 1985.62   181.4 1980.12     252 1963.75
   262.1 1962.33   302.4 1959.49   322.6 1958.52   362.9  1957.3   453.6 1955.76
   486.3 1954.69   501.3 1954.26     504 1954.22   514.1 1955.14   524.2 1957.83
   534.2 1961.47   544.3 1964.49   564.5 1969.85   574.6 1973.01   594.7 1979.84
   705.6 2020.57   816.5 2060.04   826.6 2063.95   836.6  2068.2   866.9 2081.59
#Mann= 3 , 0 , 0
       0     .06       0   486.3    .045       0   501.3      .1       0
Bank Sta=486.3,501.3
XS Rating Curve= 0 ,0
Exp/Cntr=0.3,0.1

Type RM Length L Ch R = 1 ,12358.2 ,446.6,439,431.2
XS GIS Cut Line= 2
     2139829.432      274197.803     2140723.538      274041.044
#Sta/Elev= 30
       0 2073.62    30.3 2057.66   100.9 2019.03   131.1 2003.73   171.5 1985.23
   191.6 1977.31   211.8 1970.38   262.2 1954.96   272.3 1952.34   282.4 1950.73
   383.3 1946.94     397 1946.04     412 1944.86   413.5 1944.76   423.6 1944.93
   453.9 1948.22   504.3 1949.54   524.5 1952.37   544.6 1956.62   564.8 1961.77
   615.2 1976.11   665.7 1989.64   685.8 1995.93   716.1 2007.05   746.4 2019.62
   786.7 2038.14   806.9 2048.04   827.1 2058.69   847.2 2070.15   907.7 2107.94
#Mann= 3 , 0 , 0
       0     .06       0     397    .045       0     412      .1       0
Bank Sta=397,412
XS Rating Curve= 0 ,0
Exp/Cntr=0.3,0.1

Type RM Length L Ch R = 1 ,11919.1 ,234.4,236.4,235.1
XS GIS Cut Line= 2
     2140026.832      274650.662     2140810.626       274273.28
#Sta/Elev= 30
       0 2085.38      10 2077.55      50 2044.67      70 2029.24     130 1988.94
     140 1980.37     160 1959.08     170  1950.2     180 1944.97     190  1942.7
     210 1941.48     220 1940.02     240 1935.79   251.1 1933.86     260 1933.32
   266.1 1933.48     340 1936.56     410 1940.81     440 1943.06     460 1945.71
     470 1947.66     490 1952.39     500 1955.31     520  1962.4     550 1974.56
   639.9 2017.46   739.9 2059.31   769.9 2072.69   839.9 2105.05   869.9 2117.88
#Mann= 3 , 0 , 0
       0     .06       0   251.1    .045       0   266.1     .06       0
Bank Sta=251.1,266.1
XS Rating Curve= 0 ,0
Exp/Cntr=0.3,0.1

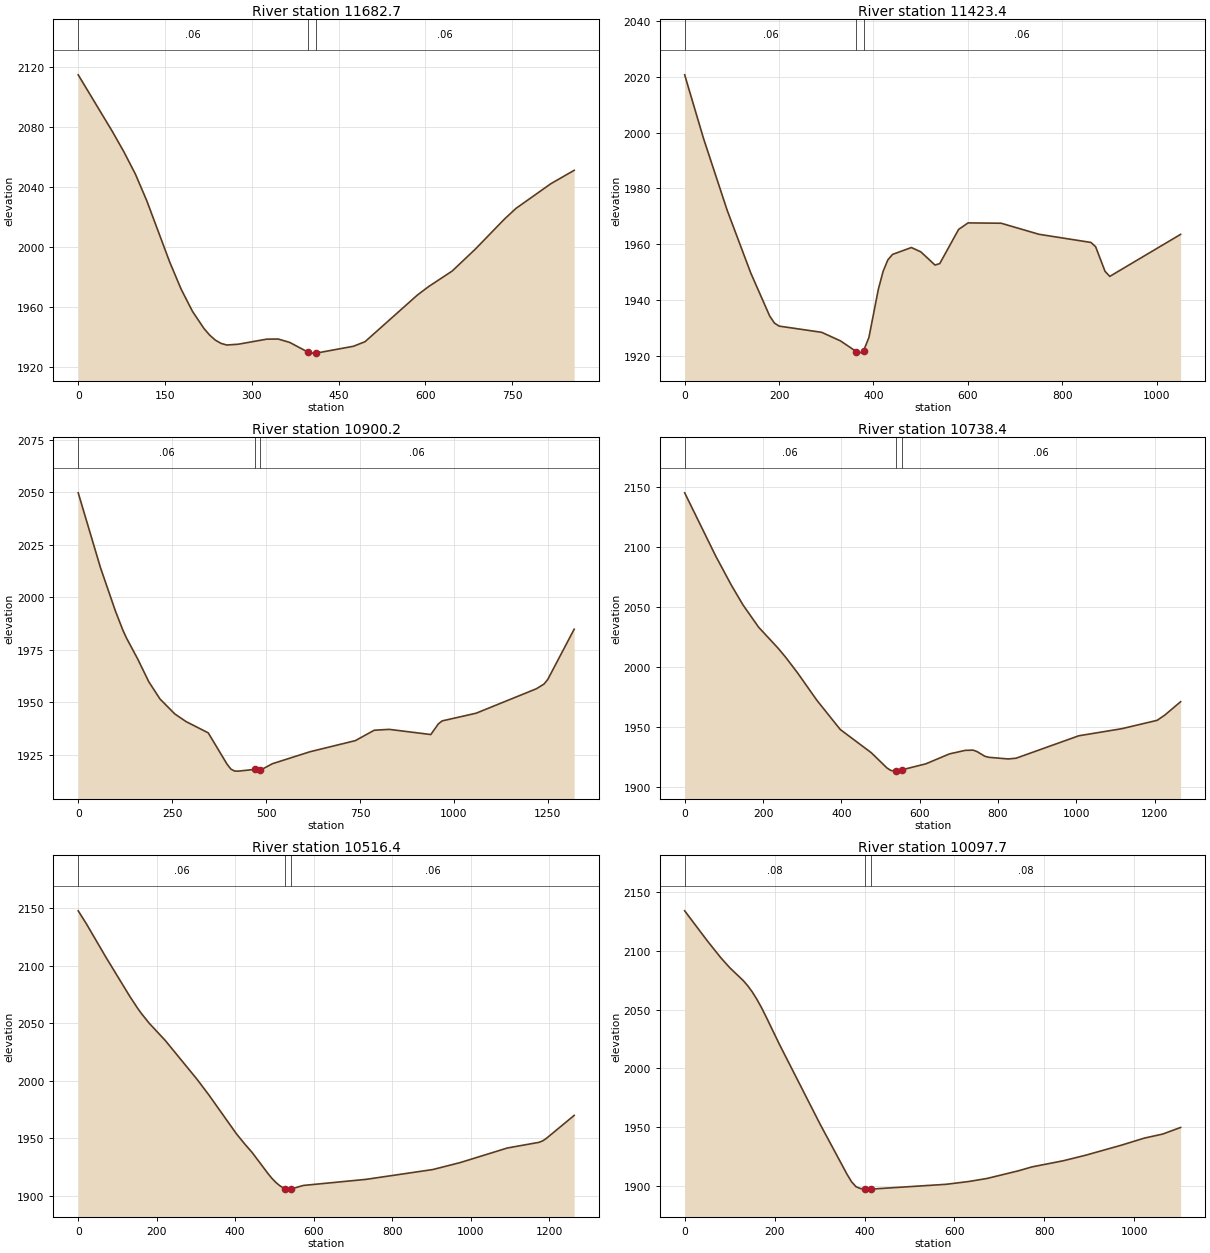
Type RM Length L Ch R = 1 ,11682.7 ,250.7,259.3,271.4
XS GIS Cut Line= 3
      2139990.26      274734.573     2140375.391      274741.359
     2140785.971      274508.923
#Sta/Elev= 30
       0 2114.67    59.3 2076.76      79 2063.36    98.8 2048.56   118.5 2030.82
     158 1990.09   177.8 1971.96   197.5 1957.11   217.3 1945.74   227.2  1941.3
     237 1937.96   246.9 1935.78   256.8 1934.72   276.6 1935.24   325.9 1938.63
   345.7 1938.69   365.4 1936.46   396.3 1930.14   405.3 1929.31   411.3 1929.33
   475.5 1933.87   495.6 1936.91     586 1967.96     606 1973.76   646.2 1983.97
   686.3 1998.61   736.5 2018.57   756.6 2025.74   816.8 2042.17     857 2051.06
#Mann= 3 , 0 , 0
       0     .06       0   396.3    .045       0   411.3     .06       0
Bank Sta=396.3,411.3
XS Rating Curve= 0 ,0
Exp/Cntr=0.3,0.1

Type RM Length L Ch R = 1 ,11423.4 ,535.6,523.2,510.7
XS GIS Cut Line= 2
     2140081.762      274965.347     2141132.627      274976.959
#Sta/Elev= 30
       0 2020.71      40 1997.85    90.1  1972.1   140.1 1949.59   180.2 1934.17
   190.2 1931.66   200.2 1930.56   290.3 1928.34   330.3 1925.25     364 1921.39
   370.3 1920.87     379 1921.68   390.4 1926.49   410.4 1943.79   420.4 1950.16
   430.4 1954.28   440.4 1956.28   480.4 1958.75   500.4  1957.2   530.5 1952.47
   540.5 1952.99   580.5 1965.26   600.5 1967.59   670.6 1967.47   750.7 1963.51
   860.8 1960.58   870.8 1959.05   890.8  1950.2   900.8  1948.4  1050.9 1963.48
#Mann= 3 , 0 , 0
       0     .06       0     364    .045       0     379     .06       0
Bank Sta=364,379
XS Rating Curve= 0 ,0
Exp/Cntr=0.3,0.1

Type RM Length L Ch R = 1 ,10900.2 ,178,161.8,145.7
XS GIS Cut Line= 3
     2140096.503      275405.427     2140415.826      275538.962
     2141251.874      275039.656
#Sta/Elev= 30
       0  2049.7    59.3 2014.08    98.9 1993.53   118.7 1984.43   128.6 1980.56
   158.2 1970.69   187.9  1959.8   217.6 1951.62   257.1 1944.49   286.8 1940.88
   346.1 1935.48   396.3 1920.54   406.4 1918.23   416.4 1917.31   426.4 1917.28
   469.4  1918.1   484.4 1917.71   516.8  1920.8   617.2 1926.52   737.6 1931.79
   787.8 1936.74     828 1937.15   938.4 1934.69   958.5 1939.77   968.6 1941.18
  1058.9 1944.83  1219.5 1956.48  1239.6  1958.7  1249.6 1960.88  1319.9 1984.81
#Mann= 3 , 0 , 0
       0     .06       0   469.4    .045       0   484.4     .06       0
Bank Sta=469.4,484.4
XS Rating Curve= 0 ,0
Exp/Cntr=0.3,0.1

Type RM Length L Ch R = 1 ,10738.4 ,192.7,222,251.3
XS GIS Cut Line= 4
     2140341.858      275982.698     2140646.271      275603.145
     2140680.951      275499.106      2141258.95      275160.013
#Sta/Elev= 30
       0 2145.37    79.4 2092.62   119.2 2068.42   148.9 2051.99   188.7 2033.45
   238.3 2016.01   258.2 2008.23     288 1995.49   337.6 1972.51   397.2  1948.2
   476.6 1928.81   516.5 1916.14   526.4 1914.07   536.4  1913.5   539.1 1913.59
   554.1 1914.52   616.2 1919.63   676.2 1927.87   716.2 1930.79   736.2 1930.99
   746.2 1929.85   766.2 1925.93   776.2 1925.03   826.3 1923.63   846.3 1924.27
  1006.3 1942.95  1116.3 1948.86  1206.3 1955.81  1226.3 1960.28  1266.3 1971.33
#Mann= 3 , 0 , 0
       0     .06       0   539.1    .045       0   554.1     .06       0
Bank Sta=539.1,554.1
XS Rating Curve= 0 ,0
Exp/Cntr=0.3,0.1

Type RM Length L Ch R = 1 ,10516.4 ,441.8,418.7,395.5
XS GIS Cut Line= 4
     2140390.024      276021.232     2140686.616      275691.452
     2140996.415      275701.527     2141333.156      275318.339
#Sta/Elev= 30
       0 2147.82    20.2  2136.9    70.6 2107.45     131 2073.63   151.2 2063.13
   161.3 2058.32   181.4 2049.82   221.8 2034.99   302.4 2001.38   332.6 1987.75
   403.2 1953.74   423.4 1945.27   443.5 1937.38   483.5  1919.2   493.5 1915.01
   503.5  1911.5   513.5 1908.63   523.5 1906.51     528 1906.11   533.5 1905.63
     543 1905.85   573.5 1908.83   733.5 1914.14   903.5 1922.67   973.6 1928.76
  1093.6 1941.44  1173.6 1946.32  1183.6 1947.65  1193.6 1949.99  1263.6 1969.79
#Mann= 3 , 0 , 0
       0     .06       0     528    .045       0     543     .06       0
Bank Sta=528,543
XS Rating Curve= 0 ,0
Exp/Cntr=0.3,0.1

Type RM Length L Ch R = 1 ,10097.7 ,557.1,541.9,526.9
XS GIS Cut Line= 2
     2140729.344      276392.428     2141333.156      275469.292
#Sta/Elev= 30
       0 2134.07    50.1 2108.68    80.2 2094.27   100.3 2085.68   130.4 2074.69
   140.4 2070.29   150.4 2065.06   160.4 2058.94   170.5 2052.01   180.5 2044.44
   210.6 2020.63   300.8 1952.94     361 1910.09     371 1903.73   381.1 1899.42
   391.1 1897.85   400.2 1897.57   411.2 1897.38   415.2 1897.42   581.6 1901.48
   631.8 1903.86   671.9  1906.4   742.1 1912.93   772.2 1916.26   842.4 1921.53
   892.5 1926.28   972.7 1934.91  1022.8 1940.82    1063 1944.18  1103.1 1949.83
#Mann= 3 , 0 , 0
       0     .08       0   400.2    .045       0   415.2     .08       0
Bank Sta=400.2,415.2
XS Rating Curve= 0 ,0
Exp/Cntr=0.3,0.1

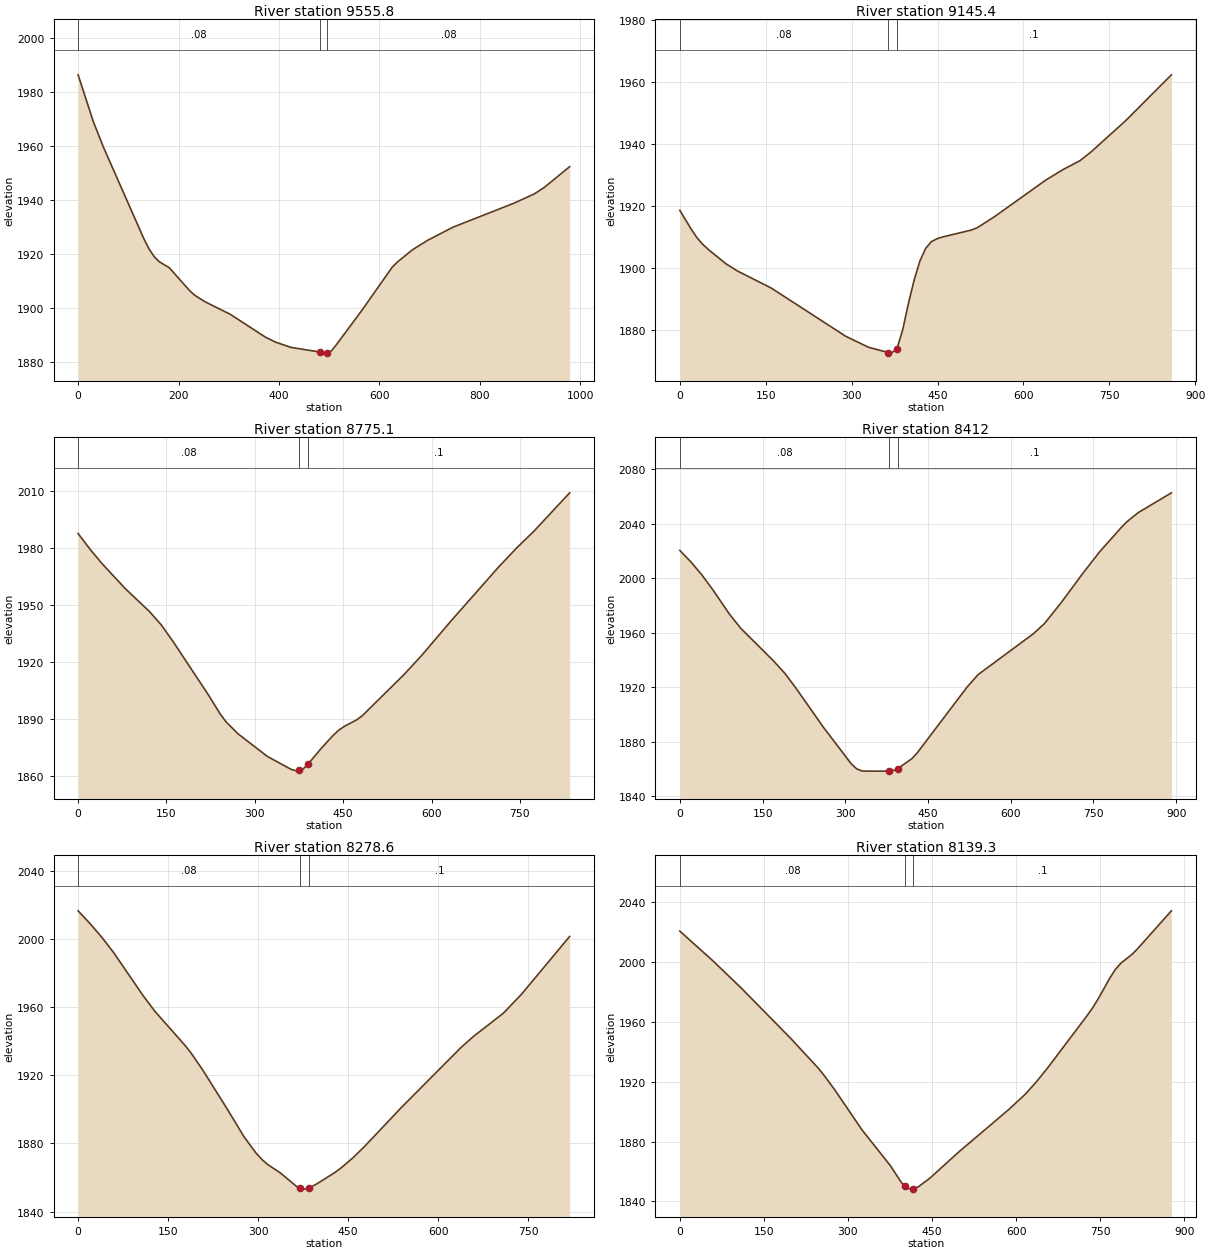
Type RM Length L Ch R = 1 ,9555.8  ,395,410.5,425.4
XS GIS Cut Line= 2
     2141501.527      276514.351     2141420.244      275538.962
#Sta/Elev= 30
       0 1986.25    30.3  1968.9    50.4 1959.49   131.2 1925.46   141.3 1921.81
   151.4 1918.98   161.4 1917.12   181.6 1914.85     222 1906.38   232.1 1904.68
   252.3 1902.31   302.7 1897.65   373.4 1889.12   393.5 1887.29   423.8 1885.38
   480.7 1883.67   494.4 1883.25   495.7 1883.36   504.5  1884.1   514.6 1886.43
   565.1  1899.1   625.6 1915.09   635.7 1916.96     666 1921.53   696.2 1925.02
   746.7 1929.88   867.8 1938.73   908.1 1942.14   928.3 1944.58   978.8 1952.26
#Mann= 3 , 0 , 0
       0     .08       0   480.7    .045       0   495.7     .08       0
Bank Sta=480.7,495.7
XS Rating Curve= 0 ,0
Exp/Cntr=0.3,0.1

Type RM Length L Ch R = 1 ,9145.4  ,370.4,370.2,370.1
XS GIS Cut Line= 2
     2141629.256      276409.845     2142087.921       275684.11
#Sta/Elev= 30
       0 1918.54      20 1912.43      30 1909.68    39.9 1907.58    49.9  1905.9
    79.9 1901.38    99.8 1899.05   159.7 1893.44   289.5  1877.9   329.4 1874.33
   364.2 1872.61   369.4 1872.43   379.2 1873.86   389.3 1880.05   399.3 1888.58
   409.3 1896.12   419.3 1902.24   429.3 1906.26   439.2 1908.45   449.2  1909.4
   459.2 1909.97   509.1  1912.2   519.1 1912.92   549.1 1916.46   638.9 1928.32
   668.8 1931.69   698.8 1934.62   718.8 1937.53   778.7 1947.56   858.5 1962.35
#Mann= 3 , 0 , 0
       0     .08       0   364.2    .045       0   379.2      .1       0
Bank Sta=364.2,379.2
XS Rating Curve= 0 ,0
Exp/Cntr=0.3,0.1

Type RM Length L Ch R = 1 ,8775.1  ,360.3,363.1,366
XS GIS Cut Line= 2
     2141960.192      276578.216     2142401.439      275869.898
#Sta/Elev= 30
       0 1987.58    20.1 1979.35    40.2  1971.9    80.4 1958.49   120.6 1946.74
   140.8 1939.68   160.9 1930.92   221.2 1902.76   241.3 1892.68   251.4  1888.5
   271.5  1882.3   321.7 1870.33     362 1863.56     372 1862.68   375.6 1863.09
   382.1 1863.83   390.6 1866.46   412.2 1874.45   432.3 1881.24   442.4  1884.2
   452.4  1886.3   472.6 1889.57   482.6 1891.85     553 1913.35   583.2 1923.46
   633.4 1941.72   713.9 1969.97     744 1979.82   774.2  1988.9   834.5 2008.95
#Mann= 3 , 0 , 0
       0     .08       0   375.6    .045       0   390.6      .1       0
Bank Sta=375.6,390.6
XS Rating Curve= 0 ,0
Exp/Cntr=0.3,0.1

Type RM Length L Ch R = 1 ,8412    ,129.3,133.5,137.6
XS GIS Cut Line= 2
     2142221.456      276752.392     2142784.627      276061.492
#Sta/Elev= 30
       0 2020.34      20 2011.96    40.1 2002.31    60.1 1991.29    90.1 1973.49
   110.2 1963.28   170.3 1939.01   190.3 1930.15   210.3 1919.36   260.4 1890.46
   310.5 1863.82   320.5    1860   330.5 1858.36   340.5 1858.28   379.9 1858.29
   390.6  1859.1   394.9 1860.09   420.6 1867.37   430.6 1871.76   520.8 1919.97
   540.8 1929.15     641 1959.16     661 1966.56     691 1981.73   731.1  2003.7
   761.2 2019.33   801.2 2037.53   811.2 2041.59   831.3 2048.14   891.4 2062.67
#Mann= 3 , 0 , 0
       0     .08       0   379.9    .045       0   394.9      .1       0
Bank Sta=379.9,394.9
XS Rating Curve= 0 ,0
Exp/Cntr=0.3,0.1

Type RM Length L Ch R = 1 ,8278.6  ,137.9,139.2,140.6
XS GIS Cut Line= 3
     2142249.075      276759.204     2142505.923      276592.307
     2142897.156       276260.68
#Sta/Elev= 30
       0 2016.38    19.8 2008.95    39.5 2000.87    59.3 1991.86   108.7 1966.47
   128.4  1957.3   177.9 1937.62   187.7  1933.3   207.5 1923.18     247 1901.05
   276.7 1883.85   296.4 1874.43   306.3 1870.63   316.4 1867.55   336.5  1862.9
   366.6  1854.1   370.6 1853.76   376.7 1853.24   385.6 1854.04   396.8  1856.1
     427 1862.77     437 1865.32   457.2 1871.33   477.3 1878.23   537.6 1900.68
   638.2 1936.28   658.3 1942.58   708.6 1956.35   738.7 1967.37   819.2 2001.37
#Mann= 3 , 0 , 0
       0     .08       0   370.6    .045       0   385.6      .1       0
Bank Sta=370.6,385.6
XS Rating Curve= 0 ,0
Exp/Cntr=0.3,0.1

Type RM Length L Ch R = 1 ,8139.3  ,298.4,320.8,343.1
XS GIS Cut Line= 3
     2142250.486      276775.616      2142569.81      276711.751
     2143011.057      276380.816
#Sta/Elev= 30
       0 2020.75    59.2 2000.81   108.6 1983.04   197.4 1949.19   246.7 1929.24
   256.6 1924.68   276.3 1914.69   325.6 1887.56   375.8 1863.87   395.8 1852.43
   401.9 1850.24   405.9  1848.8   415.9 1848.22   416.9 1848.38   425.9 1849.86
     446 1855.49   496.1 1872.54   586.4 1901.28   616.5 1911.72   636.5  1920.1
   656.6 1929.42   726.8 1964.25   736.8 1969.58   746.8  1975.6   766.9 1989.09
   776.9    1995     787 1999.32     807 2005.22     817 2009.04   877.2 2034.32
#Mann= 3 , 0 , 0
       0     .08       0   401.9    .045       0   416.9      .1       0
Bank Sta=401.9,416.9
XS Rating Curve= 0 ,0
Exp/Cntr=0.3,0.1