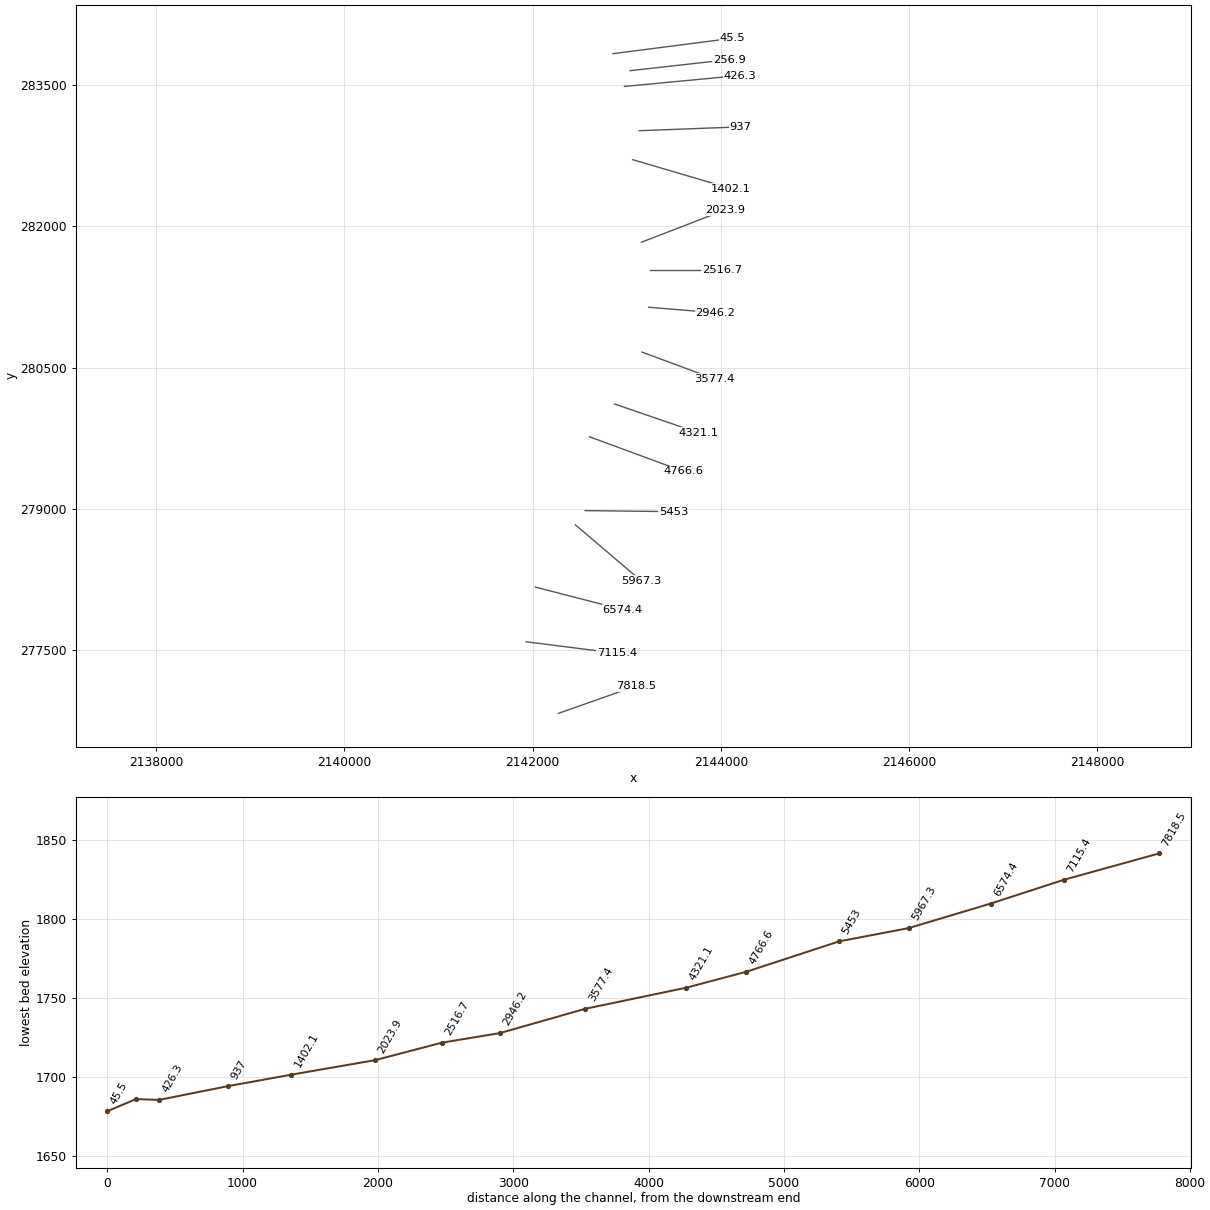
HEC-RAS study HowardCkT1.prj: HowardCkT1

--- HowardCkT1.g01 (geometry) --- (continued)

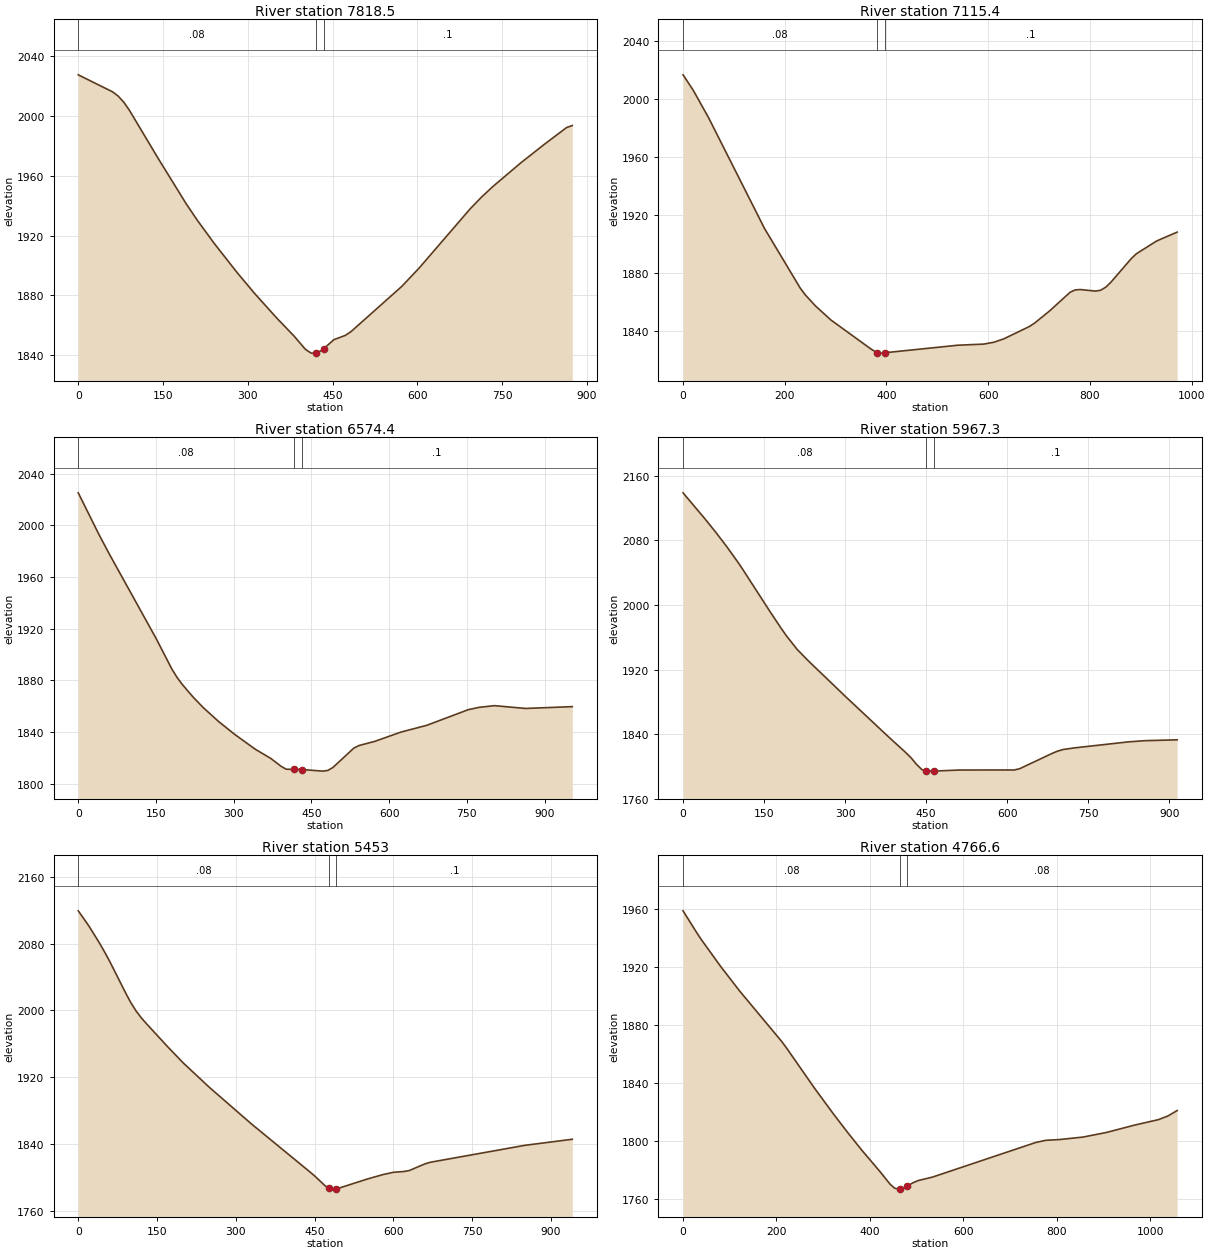
Type RM Length L Ch R = 1 ,7818.5  ,713.9,703.1,692.1
XS GIS Cut Line= 2
     2142273.709      276827.869     2143098.145      277118.163
#Sta/Elev= 30
       0 2027.19    60.3 2015.93    70.3 2013.15    80.4 2009.01    90.4 2003.63
   140.6 1971.93   190.9  1941.2     211 1929.99   241.1 1914.46   281.3 1895.17
   311.4 1881.61   351.6 1864.76   381.8 1852.92   401.9 1844.06   411.9 1841.57
   420.9 1841.54     432 1843.64  434.21 1844.46   452.1  1850.5   472.2 1853.33
   482.2 1855.78   572.6 1886.15   602.8 1898.19   693.2 1937.75   713.3 1945.58
   733.4 1952.65   783.6 1968.69   823.8 1980.62     864 1992.05     874 1993.36
#Mann= 3 , 0 , 0
       0     .08       0   420.9    .045       0  434.21      .1       0
Bank Sta=420.9,434.21
XS Rating Curve= 0 ,0
Exp/Cntr=0.3,0.1

Type RM Length L Ch R = 1 ,7115.4  ,543.9,541.1,538.1
XS GIS Cut Line= 2
     2141931.162       277588.44     2142894.939      277466.516
#Sta/Elev= 30
       0 2016.62      20    2006    50.1 1987.13   160.2 1910.75   230.4 1869.67
   240.4    1865   260.4 1857.38   290.4 1847.79   370.6 1827.42   381.6 1825.18
   390.6 1824.87   396.6 1825.13   540.8 1830.33   590.9 1831.08   610.9 1832.34
     631 1834.75     681 1843.21     691  1845.5   721.1 1854.06   761.1 1866.83
   771.2 1868.43   781.2 1868.68   811.2 1867.61   821.2 1868.22   831.2 1870.31
   841.3 1873.72   881.3    1890   891.3 1893.32   931.4 1902.18   971.5 1908.24
#Mann= 3 , 0 , 0
       0     .08       0   381.6    .045       0   396.6      .1       0
Bank Sta=381.6,396.6
XS Rating Curve= 0 ,0
Exp/Cntr=0.3,0.1

Type RM Length L Ch R = 1 ,6574.4  ,617.3,607.1,596.8
XS GIS Cut Line= 2
     2142029.862      278169.028     2142952.998      277930.987
#Sta/Elev= 30
       0  2025.1    40.1 1992.77    60.2 1977.59   150.5 1912.23   180.6 1888.79
   190.7 1882.27   200.7 1876.87   220.8 1867.45   240.8 1859.08     271 1848.12
     301 1838.49   341.2 1826.82   371.3 1819.68   391.4 1813.52   401.4 1811.26
   416.8 1811.15   431.8 1811.03   471.6 1809.79   481.7 1810.32   491.7 1812.72
   531.9 1827.64   541.9 1829.62     572 1832.78   622.2 1839.94   672.4 1845.22
   752.6 1857.33   772.7 1859.09   802.8 1860.45     863 1858.28   953.3 1859.68
#Mann= 3 , 0 , 0
       0     .08       0   416.8    .045       0   431.8      .1       0
Bank Sta=416.8,431.8
XS Rating Curve= 0 ,0
Exp/Cntr=0.3,0.1

Type RM Length L Ch R = 1 ,5967.3  ,498.7,514.3,530
XS GIS Cut Line= 2
     2142453.692      278830.899     2143150.398      278238.699
#Sta/Elev= 30
       0 2138.99    40.2 2107.01    60.3 2090.33    80.4 2072.76   100.5 2054.03
   110.5 2044.13   160.8 1992.04   180.9 1971.78   190.9 1962.22     211 1945.15
   231.1 1931.33   301.4 1886.17   381.8 1835.75     412 1817.35     422 1810.75
   432.1 1802.59   442.1 1796.07   449.8 1794.71   462.2 1794.23   464.8 1794.32
   512.5 1795.61   612.9 1795.63     623 1797.22   683.3 1816.26   693.3 1819.04
   703.4 1820.99   723.5 1822.96     824 1830.46   854.1 1831.94   914.4 1833.01
#Mann= 3 , 0 , 0
       0     .08       0   449.8    .045       0   464.8      .1       0
Bank Sta=449.8,464.8
XS Rating Curve= 0 ,0
Exp/Cntr=0.3,0.1

Type RM Length L Ch R = 1 ,5453    ,694.6,686.4,677.7
XS GIS Cut Line= 2
     2142558.198      278981.852     2143498.751       278970.24
#Sta/Elev= 30
       0 2119.15      20 2101.27      40 2081.02      50 2070.07      60 2058.52
    90.1 2020.95   100.1 2009.22   110.1 1999.18   120.1 1990.97   130.1  1983.8
   170.1 1956.45   200.1 1936.83   250.2  1907.4   330.2 1863.67   440.3 1806.81
   450.3 1801.52   470.3 1789.62   476.5 1787.32   480.3 1785.91   490.3 1785.81
   491.5 1786.03   550.4 1797.92   580.4 1803.29   600.4 1805.98   620.4 1806.94
   630.4 1808.11   660.4 1816.15   670.4    1818   850.6  1838.3   940.6 1845.55
#Mann= 3 , 0 , 0
       0     .08       0   476.5    .045       0   491.5      .1       0
Bank Sta=476.5,491.5
XS Rating Curve= 0 ,0
Exp/Cntr=0.3,0.1

Type RM Length L Ch R = 1 ,4766.6  ,445.1,445.6,446.3
XS GIS Cut Line= 2
     2142604.645      279765.647     2143597.451      279399.876
#Sta/Elev= 30
       0 1958.76    30.2  1943.2    40.3 1938.36    80.6 1920.32   120.9 1903.49
   211.6 1868.39   221.7 1863.97   282.1 1835.99   322.4  1818.3   352.7 1805.56
   382.9 1793.39   423.2 1778.09   443.4 1769.92   453.4  1767.1   463.5 1766.54
   464.3 1766.63   473.6 1767.63   479.3 1768.61   493.8 1771.14   503.8 1772.48
   534.1 1774.85   755.7  1798.8   775.9 1800.21   806.1 1800.78   856.5  1802.5
   906.9  1805.7   967.4  1810.8  1017.7 1814.51  1037.9 1817.01    1058 1820.79
#Mann= 3 , 0 , 0
       0     .08       0   464.3    .045       0   479.3     .08       0
Bank Sta=464.3,479.3
XS Rating Curve= 0 ,0
Exp/Cntr=0.3,0.1

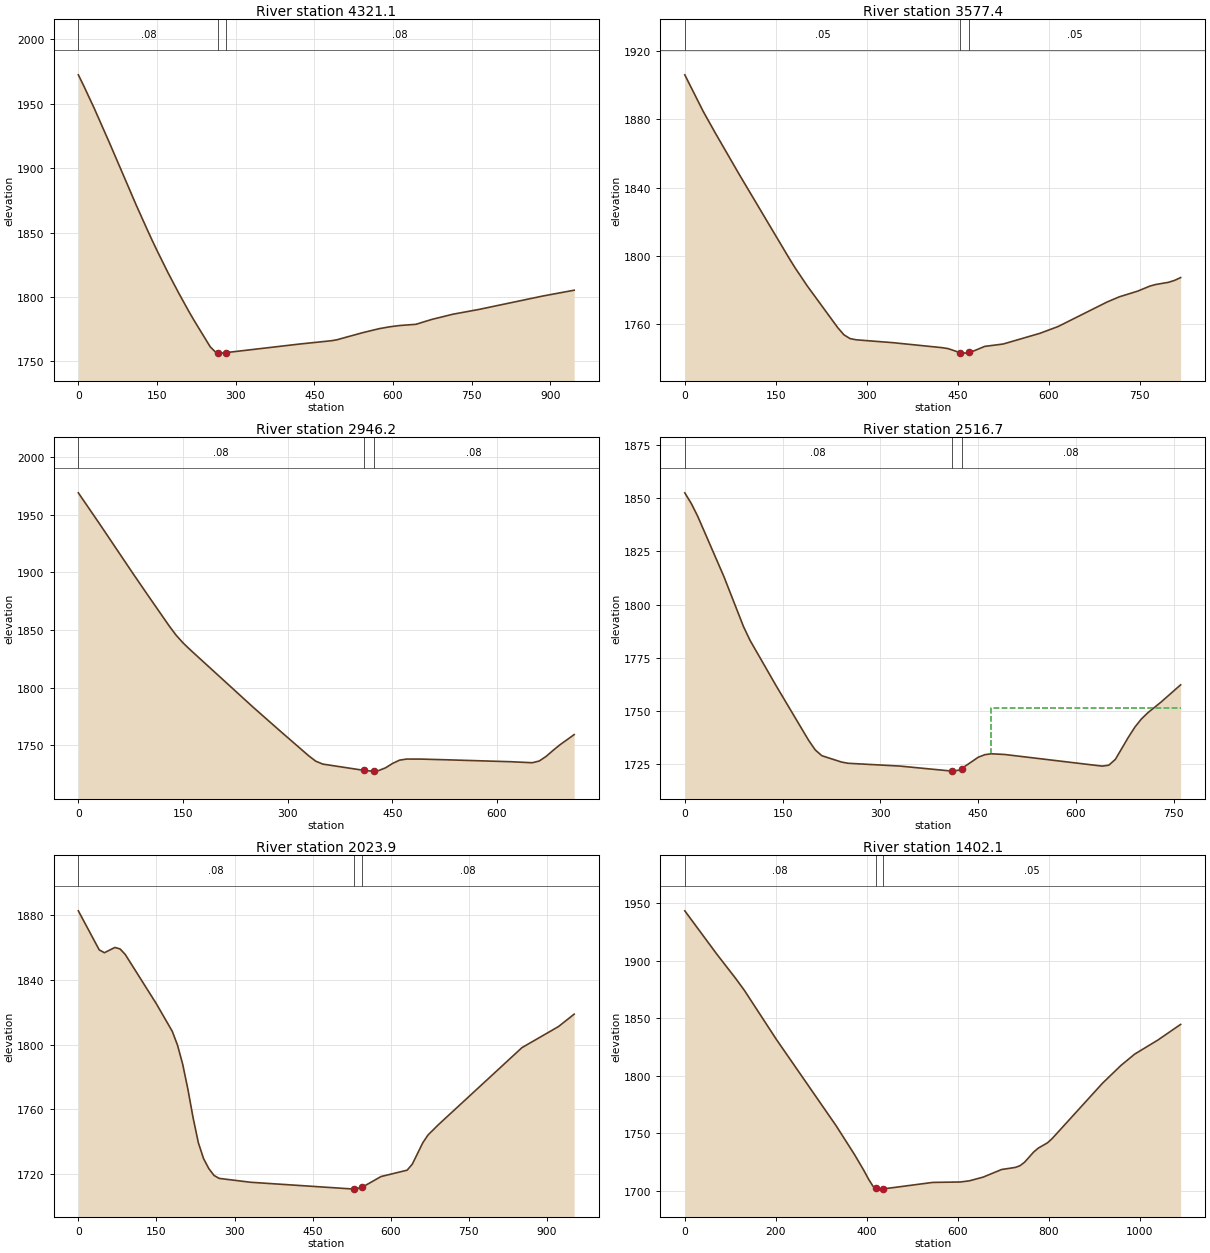
Type RM Length L Ch R = 1 ,4321.1  ,742.9,743.7,744
XS GIS Cut Line= 2
     2142871.716         280114.     2143765.822      279806.288
#Sta/Elev= 30
       0 1972.52    10.1 1964.17    30.2 1946.63    60.4 1918.77   110.6 1871.19
   130.8  1852.9   140.8 1844.01   150.9 1835.42     171 1818.89   191.1 1803.34
   211.2 1788.51   221.3 1781.46   251.5 1761.37   261.5 1757.27   267.1  1756.8
   271.6 1756.43   282.1 1756.85   422.5 1763.51   482.8 1766.06   492.9 1766.78
   543.2  1772.4   573.4 1775.39   593.5 1776.85   613.6  1777.9   643.8  1778.8
     674 1782.59   714.2 1786.62   764.5  1790.4   885.2 1800.72   945.6 1805.28
#Mann= 3 , 0 , 0
       0     .08       0   267.1    .045       0   282.1     .08       0
Bank Sta=267.1,282.1
XS Rating Curve= 0 ,0
Exp/Cntr=0.3,0.1

Type RM Length L Ch R = 1 ,3577.4  ,625.7,631.2,637.1
XS GIS Cut Line= 2
      2143162.01      280665.559     2143928.387       280381.07
#Sta/Elev= 30
       0 1905.95    30.3  1884.6    50.5 1871.79    90.8 1847.06   171.6 1798.89
   181.7 1793.11   201.8 1782.49   252.3 1757.96   262.4 1753.82   272.5  1751.6
   282.6 1750.91   343.1 1749.23   423.9 1746.32     434 1745.76     454 1743.37
   464.2 1743.11     469 1743.57   474.3 1744.07   494.5 1747.05   524.8 1748.43
   585.4 1754.69   615.6 1758.69   696.4 1773.05   716.6 1776.08   746.8  1779.4
     767 1782.36   777.1 1783.31   797.3 1784.53   807.4 1785.65   817.5 1787.31
#Mann= 3 , 0 , 0
       0     .05       0     454    .045       0     469     .05       0
Bank Sta=454,469
XS Rating Curve= 0 ,0
Exp/Cntr=0.3,0.1

Type RM Length L Ch R = 1 ,2946.2  ,427.7,429.5,431.3
XS GIS Cut Line= 2
      2143231.68      281141.641     2143939.998      281083.582
#Sta/Elev= 30
       0 1968.83      30 1942.36    80.1 1897.36   100.1 1879.76   130.1 1853.63
   140.1 1845.55   150.2 1838.75   160.2 1832.96   250.2  1783.3   290.3 1761.94
   330.3 1740.96   340.3 1736.35   350.3 1733.82   409.1  1728.4   420.4 1727.72
   424.1  1727.9   430.4  1728.2   440.4 1730.59   450.4 1734.37   460.4 1737.22
   470.5 1738.17   490.5 1738.16   530.5 1737.49   620.6 1735.85   650.6 1734.99
   660.6 1736.46   670.6 1740.52   680.7 1745.81   690.7  1750.7   710.7 1759.34
#Mann= 3 , 0 , 0
       0     .08       0   409.1    .045       0   424.1     .08       0
Bank Sta=409.1,424.1
XS Rating Curve= 0 ,0
Exp/Cntr=0.3,0.1

Type RM Length L Ch R = 1 ,2516.7  ,484.4,492.8,501.1
XS GIS Cut Line= 2
     2143249.098      281536.441     2144009.669      281536.441
#Sta/Elev= 30
       0 1852.54      10 1847.49      20 1841.38      60 1813.15    90.1 1789.59
   100.1 1783.15   140.1  1761.8   190.1 1736.07   200.2 1731.59   210.2  1728.9
   240.2 1725.93   250.2 1725.34   330.2 1724.01   409.5 1721.66   410.3 1721.64
   420.3 1722.09   424.5 1722.81   450.3  1728.2   460.4 1729.39   470.4 1729.79
   490.4 1729.48   640.5 1723.99   650.5 1724.45   660.5 1727.17   680.5  1737.6
   690.5 1742.36   700.5 1746.19   710.5 1749.15   730.6 1754.13   760.6 1762.23
#Mann= 3 , 0 , 0
       0     .08       0   409.5    .045       0   424.5     .08       0
#XS Ineff= 2 , 0
                          469.81         1751.32
Permanent Ineff=
       F       F
Bank Sta=409.5,424.5
XS Rating Curve= 0 ,0
Exp/Cntr=0.3,0.1

Type RM Length L Ch R = 1 ,2023.9  ,636.6,621.8,606.4
XS GIS Cut Line= 2
     2143156.204      281832.541     2144044.504      282175.089
#Sta/Elev= 30
       0 1882.71    40.1 1858.57    50.1 1856.79    70.2 1860.06    80.2 1859.13
    90.2 1855.68   150.3 1824.98   180.4 1808.18   190.4 1799.67   200.4 1787.83
   210.5 1772.19   220.5 1754.51   230.5 1739.25   240.5 1729.43   250.5 1723.32
   260.6 1719.02   270.6  1717.2   330.7 1714.82   529.6 1710.59   531.2 1710.57
   544.6 1711.65   581.3 1718.36   631.4 1722.29   641.4 1726.07   661.4 1739.21
   671.4 1744.04   691.5 1750.45   851.8 1798.07     922 1811.12   952.1 1818.79
#Mann= 3 , 0 , 0
       0     .08       0   529.6    .045       0   544.6     .08       0
Bank Sta=529.6,544.6
XS Rating Curve= 0 ,0
Exp/Cntr=0.3,0.1

Type RM Length L Ch R = 1 ,1402.1  ,457.8,465.2,472.5
XS GIS Cut Line= 2
      2143063.31       282709.23     2144108.369      282401.518
#Sta/Elev= 30
       0 1943.46    70.6 1905.64     111 1885.05   131.1 1874.16   201.7 1831.32
   332.9 1756.26   373.2 1731.23   393.4 1717.64   403.5 1710.18   413.6 1703.82
   419.4  1702.4   423.7 1701.35   434.4 1701.45   544.7 1707.19   605.2 1707.56
   625.4 1708.58   655.7 1711.82     696 1718.41   726.3 1720.25   736.4  1721.7
   746.4 1724.71   766.6 1733.66   776.7 1737.04   796.9 1741.64     807 1745.27
   917.9 1793.54   958.3 1808.96   988.6 1818.85    1039 1830.93  1089.4 1844.66
#Mann= 3 , 0 , 0
       0     .08       0   419.4    .045       0   434.4     .05       0
Bank Sta=419.4,434.4
XS Rating Curve= 0 ,0
Exp/Cntr=0.3,0.1

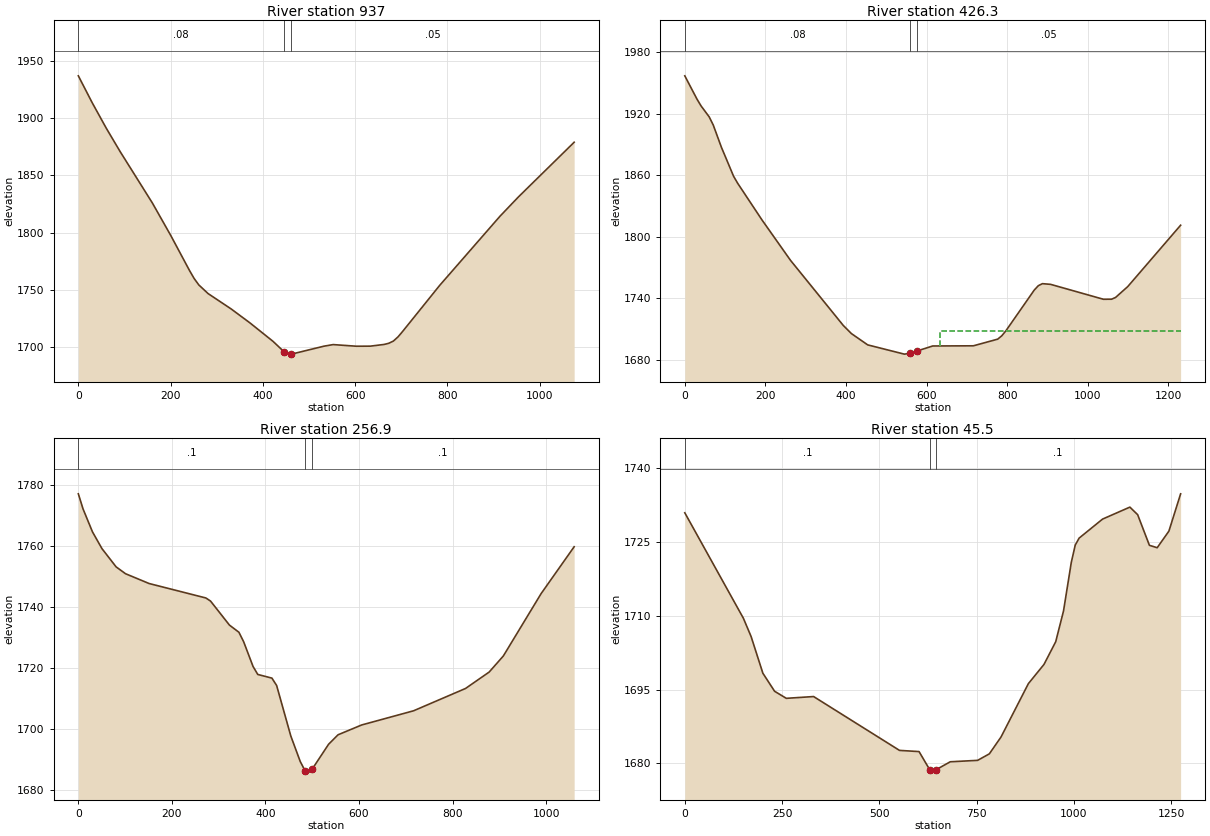
Type RM Length L Ch R = 1 ,937     ,509.4,510.7,512
XS GIS Cut Line= 2
      2143132.98      283016.942     2144207.069      283057.583
#Sta/Elev= 30
       0 1936.97    30.1 1913.48    60.3 1891.46    90.4 1871.02   160.7 1825.89
   200.9 1797.29   241.1 1767.02   251.1  1760.1   261.2  1754.5   281.3 1746.96
   331.5 1733.49   371.7 1721.49   421.9 1705.33   445.6 1696.34     452 1694.61
   460.6 1694.19   462.1 1694.12   532.4 1701.05   552.5 1702.44   602.7 1701.02
   632.9 1701.08     663 1702.57     673 1703.59   683.1 1705.55   693.1 1709.18
   703.2    1714   783.5 1754.16   914.1 1814.44   954.3 1831.39  1074.9 1879.01
#Mann= 3 , 0 , 0
       0     .08       0   445.6    .045       0   460.6     .05       0
Bank Sta=445.6,460.6
XS Rating Curve= 0 ,0
Exp/Cntr=0.3,0.1

Type RM Length L Ch R = 1 ,426.3   ,168.9,169.3,169.7
XS GIS Cut Line= 2
     2142976.221      283487.219     2144201.263      283603.336
#Sta/Elev= 30
       0 1957.13    30.3 1934.35    40.4 1927.73    60.5 1917.08    70.6  1909.1
    90.8 1887.45     121 1859.14   131.1  1852.3   191.6  1816.4   262.2 1777.05
   393.4 1713.35   413.5 1705.45   453.9 1694.42   544.7 1685.39   560.1 1686.18
   575.1 1688.29   615.3 1693.35   716.1 1693.51   776.6 1700.02   786.7 1703.32
   796.8 1708.13   867.4 1748.01   877.5 1752.26   887.6 1754.19   907.8 1753.52
  1038.9 1738.96  1059.1    1739  1069.2 1740.78  1099.4 1751.38  1230.5 1811.27
#Mann= 3 , 0 , 0
       0     .08       0   560.1    .045       0   575.1     .05       0
#XS Ineff= 2 , 0
                          632.49         1708.33
Permanent Ineff=
       F       F
Bank Sta=560.1,575.1
XS Rating Curve= 0 ,0
Exp/Cntr=0.3,0.1

Type RM Length L Ch R = 1 ,256.9   ,211,211.4,211.8
XS GIS Cut Line= 2
     2143035.618      283654.475     2144089.131      283772.487
#Sta/Elev= 30
       0 1777.17    10.1 1772.21    30.3 1764.68    50.5 1759.21    80.8 1753.22
     101 1750.97   151.4 1747.76   272.6 1743.03   282.7 1742.01   323.1 1734.13
   343.3 1731.79   353.4  1728.7   373.6 1720.56   383.7 1717.95   413.9 1716.75
     424 1714.33   454.3 1697.77   474.5  1689.4   484.9 1686.33   494.7 1685.93
   499.9 1686.89   535.1 1695.07   555.3 1698.17   605.8 1701.39   716.8 1706.04
   827.9 1713.36   878.4 1718.74   908.7 1724.01   989.4 1744.44  1060.1 1759.82
#Mann= 3 , 0 , 0
       0      .1       0   484.9    .045       0   499.9      .1       0
Bank Sta=484.9,499.9
XS Rating Curve= 0 ,0
Exp/Cntr=0.3,0.1

Type RM Length L Ch R = 1 ,45.5    ,45.5,45.5,45.5
XS GIS Cut Line= 2
     2142853.953      283835.224     2144117.497      283998.113
#Sta/Elev= 30
       0 1730.87   150.5 1709.47   170.5 1705.73   200.6 1698.31   230.7 1694.65
   260.8 1693.21     331 1693.57   551.7 1682.64   601.9  1682.4   629.5  1678.7
     632 1678.23   644.5 1678.67   682.1 1680.33   752.4 1680.62   782.5 1681.94
   812.6 1685.37   882.8 1696.19   922.9 1700.09     953 1704.69   973.1 1710.94
   993.1 1720.81  1003.2 1724.31  1013.2 1725.73  1073.4 1729.59  1143.6 1732.02
  1163.6 1730.49  1193.8 1724.27  1213.8 1723.78  1243.9 1727.15    1274 1734.72
#Mann= 3 , 0 , 0
       0      .1       0   629.5    .045       0   644.5      .1       0
Bank Sta=629.5,644.5
XS Rating Curve= 0 ,0
Exp/Cntr=0.3,0.1

Chan Stop Cuts=-1
Use User Specified Reach Order=0
Composite Channel Slope=5